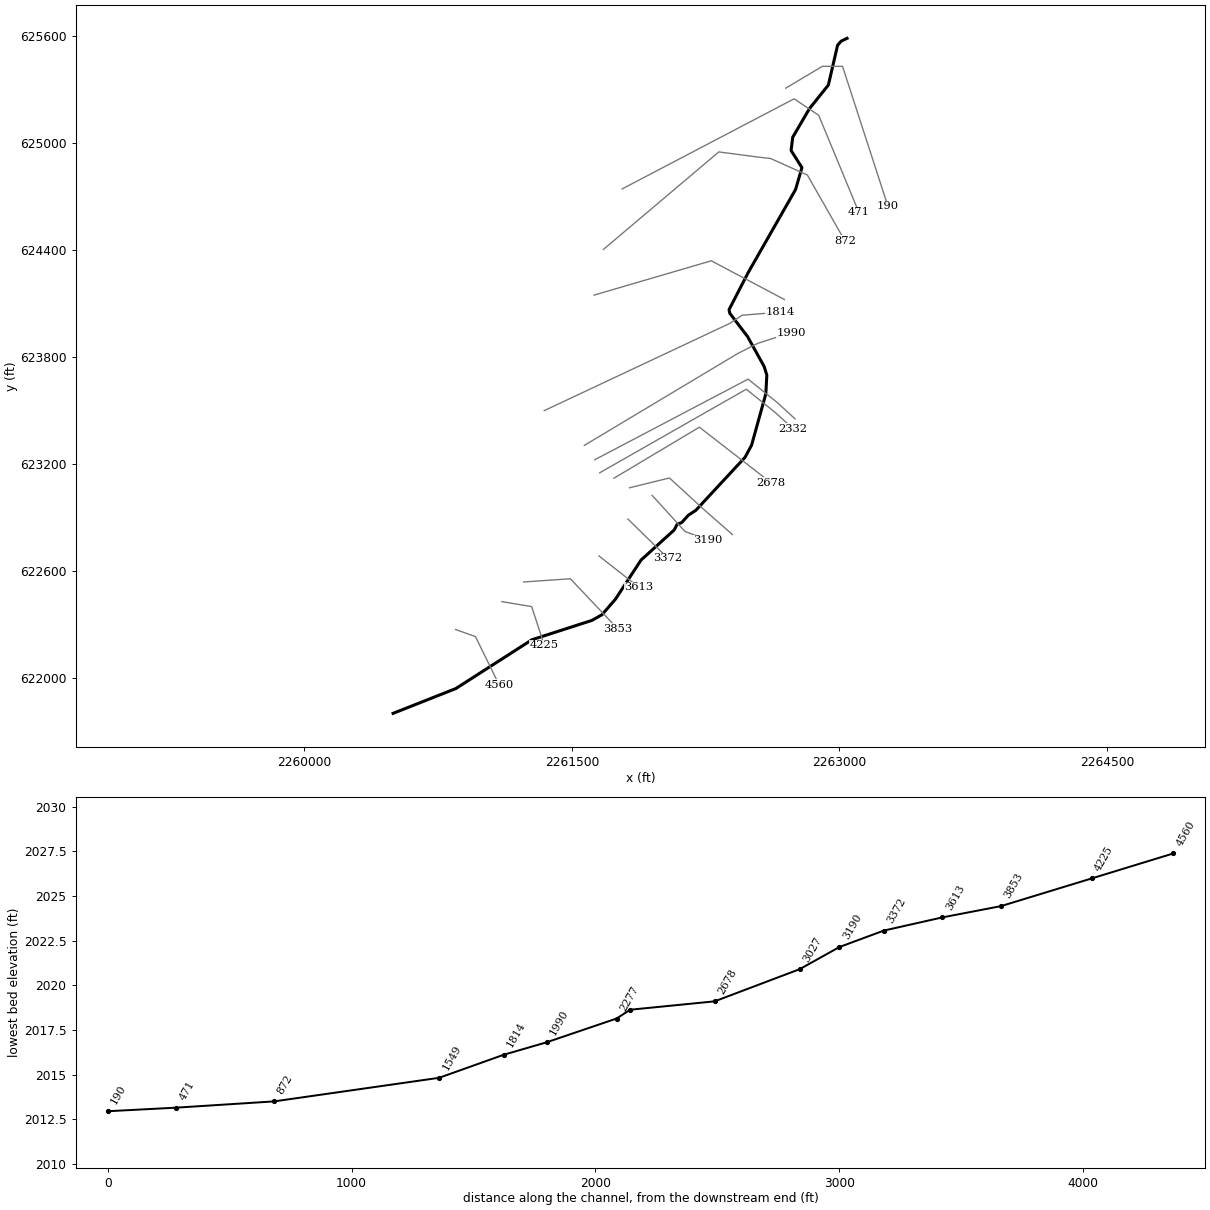
--- TYGVRV2T1.prj (project) ---

Proj Title=TYGVRV2T1
Current Plan=p01
Default Exp/Contr=0,0
English Units
Geom File=g01
Flow File=f01
Plan File=p01
BEGIN DESCRIPTION:
----------MODEL BY WOOD PLC 2022----------
AFH study
Randolph County, WV
HEC-RAS Version: RAS 6.2
Vertical Datum: NAVD88
Projection: NAD 1983 StatePlane West Virginia S FIPS 4702 (US Feet)
Terrain: 1-meter LIDAR (FEMA Region III 3DEP collected 2016-2018)
Land Use: 2019 NLCD
Hydrologic Method:
WV SIR2010-5033 regression equations
Additional Model Notes:
None
END DESCRIPTION:
DSS Export Rating Curves= 0
DSS Export Rating Curve Sorted= 0
DSS Export Volume Flow Curves= 0
DXF OffsetX= 0
DXF OffsetY= 0
DXF ScaleX= 0
DXF ScaleY= 0

--- TYGVRV2T1.p01 (plan) ---

Plan Title=Floodplain
Program Version=6.20
Short Identifier=Floodplain
Geom File=g01
Flow File=f01
Subcritical Flow
K Sum by GR= 0
Std Step Tol= 0.01
Critical Tol= 0.01
Num of Std Step Trials= 20
Max Error Tol= 0.3
Flow Tol Ratio= 0.001
Split Flow NTrial= 30
Split Flow Tol= 0.02
Split Flow Ratio= 0.02
Log Output Level= 0
Friction Slope Method= 1
Unsteady Friction Slope Method= 2
Unsteady Bridges Friction Slope Method= 1
Parabolic Critical Depth
Global Vel Dist= 0 , 0 , 0
Global Log Level= 0
CheckData=True
Encroach Param=-1 ,0,0, 0
Mapping Interval=1HOUR
Computation Time Step Use Courant=        0
Computation Time Step Use Time Series=    0
Computation Time Step Count To Double=0
Computation Time Step Max Doubling=0
Computation Time Step Max Halving=0
Computation Time Step Residence Courant=0
Run HTab= 0
Run UNet= 0
Run Sediment= 0
Run PostProcess= 0
Run WQNet= 0
Run RASMapper=-1
UNET Theta= 0
UNET Theta Warmup= 0
UNET ZTol= 0
UNET ZSATol= 0
UNET MxIter= 0
UNET Max Iter WO Improvement= 0
UNET MaxInSteps= 0
UNET DtIC= 0
UNET DtMin= 0
UNET MaxCRTS= 0
UNET WFStab= 0
UNET SFStab= 0
UNET WFX= 1
UNET SFX= 1
UNET Gravity=32.174
UNET 1D Methodology=Finite Difference
UNET DSS MLevel= 1
UNET Pardiso=0
UNET DZMax Abort= 0
UNET Use Existing IB Tables= 0
UNET Froude Reduction=False
UNET Froude Limit= 0
UNET Froude Power= 0
UNET D1 Cores= 0
UNET WindReference=Eulerian
UNET WindDragFormulation=Hsu (1988)
UNET D2 Coriolis=0
UNET D2 Cores= 0
UNET D2 Theta= 1
UNET D2 Theta Warmup= 1
UNET D2 Z Tol= 0.01
UNET D2 Volume Tol= 0.01
UNET D2 Max Iterations= 20
UNET D2 Equation= 0
UNET D2 RampUpFraction=0.1
UNET D2 TimeSlices= 1
UNET D2 Turbulence Formulation=Non-Conservative (original)
UNET D2 Eddy Viscosity=0.3
UNET D2 Transverse Eddy Viscosity=0.1
UNET D2 Smagorinsky Mixing=0
UNET D2 BCVolumeCheck=0
UNET D2 Cores=0
UNET D2 SolverType=PARDISO (Direct)
UNET D2 Minimum Iterations= 2147483647
UNET D2 Maximum Iterations= 2147483647
UNET D2 Restart Number= 10
UNET D2 Relaxation Coeff=1.3
UNET D2 SOR Precondition Iterations= 10
UNET D2 ILUT Maximum Fill= 8
UNET D2 ILUT Tolerance=1E-08
UNET D1D2 MaxIter= 0
UNET D1D2 ZTol=0.01
UNET D1D2 QTol=0.1
UNET D1D2 MinQTol=1
Write IC File= 0
Write IC File at Fixed DateTime=0
Write IC File at Sim End=0
Echo Input=False
Echo Parameters=False
Echo Output=False
Write Detailed= 0
HDF Write Warmup=0
HDF Write Time Slices=0
HDF Flush=0
HDF Compression= 1
HDF Chunk Size= 1
HDF Spatial Parts= 1
HDF Use Max Rows=0
HDF Fixed Rows= 1
Calibration Method= 0
Calibration Iterations= 20
Calibration Max Change=0.05
Calibration Tolerance=0.2
Calibration Maximum=1.5
Calibration Minimum=0.5
Calibration Optimization Method= 1
WQ AD Non Conservative
WQ ULTIMATE=-1
WQ Max Comp Step=1HOUR
WQ Output Interval=15MIN
WQ Output Selected Increments= 0
WQ Output face flow=0
WQ Output face velocity=0
WQ Output face area=0
WQ Output face dispersion=0
WQ Output cell volume=0
WQ Output cell surface area=0
WQ Output cell continuity=0
WQ Output cumulative cell continuity=0
WQ Output face conc=0
WQ Output face dconc_dx=0
WQ Output face courant=0
WQ Output face peclet=0
WQ Output face adv mass=0
WQ Output face disp mass=0
WQ Output cell mass=0
WQ Output cell source sink temp=0
WQ Output nsm pathways=0
WQ Output nsm derived pathways=0
WQ Create Restart=0
WQ Fixed Restart=0
WQ System Summary=0
WQ Write To DSS=0
Sorting and Armoring Iterations= 10
XS Update Threshold= 0.02
Bed Roughness Predictor= 0
Hydraulics Update Threshold= 0.02
Energy Slope Method= 1
Volume Change Method= 1
Sediment Retention Method= 0
Sediment TS Multiplier= 1
Warm Up Method= 0
XS Weighting Method= 0
Number of US Weighted Cross Sections= 1
Number of DS Weighted Cross Sections= 1
Upstream XS Weight=0
Main XS Weight=1
Downstream XS Weight=0
Number of DS XS's Weighted with US Boundary= 1
Upstream Boundary Weight= 1
Weight of XSs Associated with US Boundary= 0
Number of US XS's Weighted with DS Boundary= 1
Downstream Boundary Weight= 0.5
Weight of XSs Associated with DS Boundary= 0.5
Percentile Method= 0
Sediment Output Level= 3
Mass or Volume Output= 0
Output Increment Type= 1
Profile and TS Output Increment= 1
Transport Output Increment 1
XS Output Flag= 0
XS Output Increment= 10
Read HDF5 Sediment Hotstart= 0
Sediment Hotstart Type= 0
Write Gradation File= 0
Read Gradation Hotstart= 0
Write HDF5 File= 1
Write Binary Output= 1
Write DSS Sediment File= 0
DSS Sediment Output Type= 1
SV Curve= 0
Specific Gage Flag= 0
Subcell Erosion Methods= 0
Subcell Deposition Methods= 0
Advection Scheme= 1
Matrix Solver= 0
Implicit Weighting Factor= 1
Maximum Outer Loop Convergence Iterations= 5
Convergence Maximum Absolute= 0.001
Convergence RMSE= 0.0001
Grain Fractions Max Abs Error= 0.001
Max Subgrid Regions= 1
Max Subgrid Length Scale= 3.402823E+38
Initial Layer Thickness= 3.402823E+38
Min Layer Thickness= 3.402823E+38
Max Layer Thickness= 3.402823E+38
Number of Layers= 5

--- TYGVRV2T1.f01 (steady flow) ---

Flow Title=Flow
Program Version=6.20
Number of Profiles= 1
Profile Names=P100yr
River Rch & RM=TYGVRV2T1,Main,4560
     326
River Rch & RM=TYGVRV2T1,Main,3190
     462
River Rch & RM=TYGVRV2T1,Main,471
     588
Boundary for River Rch & Prof#=TYGVRV2T1,Main            , 1
Up Type= 0
Dn Type= 3
Dn Slope=0.00068
DSS Import GetInterval= 0
DSS Import GetPeak= 0
DSS Import FillOption= 0

--- TYGVRV2T1.g01 (geometry) ---

Geom Title=Geometry
Program Version=6.20

River Reach=TYGVRV2T1       ,Main
Reach XY= 30
2260497.31191623621803.1023352042260849.44399999621942.328000009
     2261275.943622215.9220000212261611.94400001622324.273000017
2261668.45499998622355.9570000172261744.23600003622443.544000015
2261887.29099999      622662.2942262073.96593444622831.837752869
2262090.22751568622863.3185062922262115.48778175622872.781372672
2262153.26399998622914.3770000042262194.46842105622941.290703511
     2262470.625623238.6830000132262507.43000001623306.738000005
2262587.29100004623594.9329999982262592.84700002623699.099000007
2262578.26299998623747.016000018     2262485.208623915.070999995
2262385.20800003624046.3219999972262381.04099999624066.459999993
     2262486.597 624271.321000012262753.95800002624740.070999995
2262789.57600002624862.9670000082262728.95800002624958.820999995
2262737.98600002625033.1270000042262831.73600003      625193.544
2262937.86400002625325.8560000212262989.59373169625549.244585211
 2263009.7459496625572.1222587082263042.62100001625587.724999994

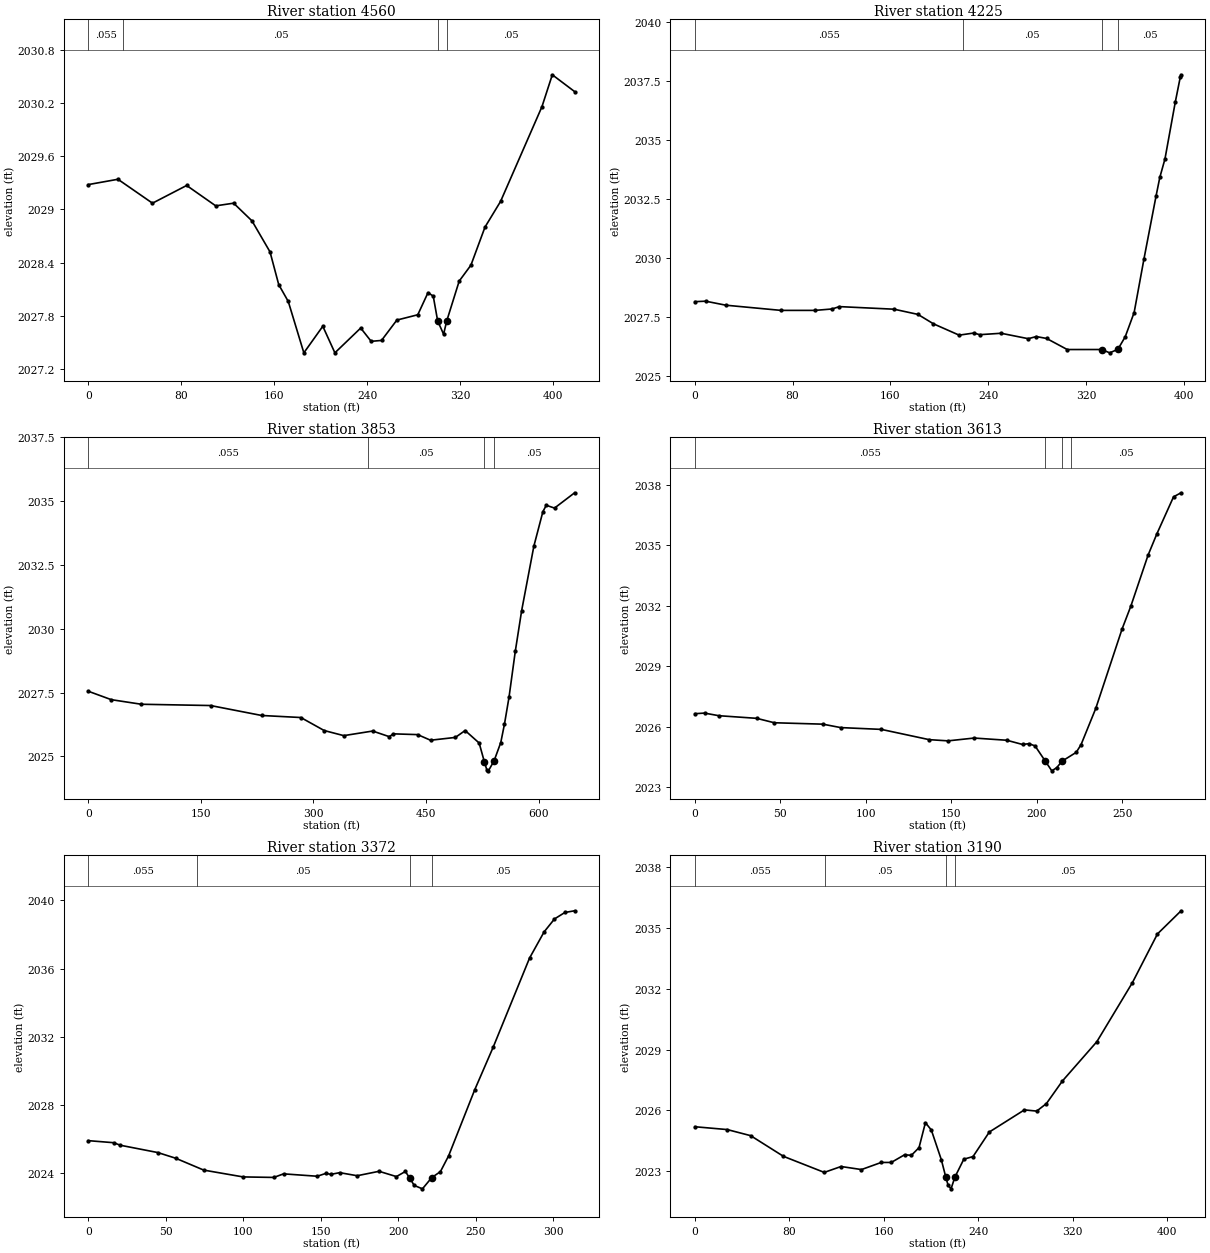
Type RM Length L Ch R = 1 ,4560    ,336.8,335.1,334.3
XS GIS Cut Line= 3
2260848.17882418 622273.136508522260959.30893901622233.761220375
2261091.39939058621963.960199589
#Sta/Elev= 30
       0 2029.28    25.5 2029.34    55.2 2029.07    84.6 2029.27   109.6 2029.04
     125 2029.07   140.8 2028.87   156.3 2028.52   163.8 2028.15     172 2027.96
   185.4 2027.38   201.7 2027.68   212.1 2027.38   234.3 2027.66   243.3 2027.51
   252.2 2027.52   265.4 2027.75   283.4 2027.81   292.2 2028.06   296.7 2028.02
   300.5 2027.74   305.6 2027.59  308.29 2027.74     319 2028.19   329.1 2028.37
   341.2  2028.8   354.6 2029.09   390.2 2030.16   399.1 2030.52   418.3 2030.33
#Mann= 4 ,-1,0
       0    .055       0      30     .05       0   300.5    .045       0
  308.29     .05       0
Bank Sta=300.5,308.29
XS Rating Curve= 0 ,0
Exp/Cntr(USF)=0,0
Exp/Cntr=0.3,0.1

Type RM Length L Ch R = 1 ,4225    ,370.8,372,376.4
XS GIS Cut Line= 3
2261107.43988621622429.6439123482261274.41277579622401.776738656
2261345.33084477 622184.67387634
#Sta/Elev= 30
       0 2028.15     8.9 2028.17    25.4    2028    70.5 2027.78    98.4 2027.78
   112.3 2027.84   118.3 2027.94     163 2027.83   182.5 2027.61   195.2 2027.21
   216.2 2026.73   228.2 2026.82     233 2026.75   250.5 2026.81   272.7 2026.58
   279.3 2026.67   287.7 2026.59   304.6 2026.12332.82692026.121   339.3 2025.98
346.0069 2026.13     352 2026.66   359.3 2027.69   367.4 2029.98   377.3 2032.65
   380.3 2033.42   384.5  2034.2   392.9  2036.6   397.1 2037.69   397.7 2037.77
#Mann= 4 ,-1,0
       0    .055       0  219.28     .05       0332.8269    .045       0
346.0069     .05       0
Bank Sta=332.8269,346.0069
XS Rating Curve= 0 ,0
Exp/Cntr(USF)=0,0
Exp/Cntr=0.3,0.1

Type RM Length L Ch R = 1 ,3853    ,239.6,240,241.7
XS GIS Cut Line= 3
2261229.68746185622539.8091856482261491.45773357622557.833857059
2261756.49311216622277.683653165
#Sta/Elev= 30
       0 2027.55    30.6 2027.22    70.7 2027.04   162.9 2026.99     231  2026.6
   283.2 2026.52   314.3 2026.01   340.4 2025.81   378.9 2025.99     401 2025.77
   406.5 2025.88   438.8 2025.85     456 2025.63   489.1 2025.74   502.1 2026.01
   520.8 2025.52527.89652024.765   531.2 2024.45   533.1 2024.43540.67622024.823
   549.6 2025.54   554.5 2026.26   560.6 2027.32   568.9 2029.11   577.4 2030.71
   593.7 2033.24   605.7 2034.59   610.2 2034.84   621.2 2034.73     648 2035.33
#Mann= 4 ,-1,0
       0    .055       0  372.39     .05       0527.8965    .045       0
540.6762     .05       0
Bank Sta=527.8965,540.6762
XS Rating Curve= 0 ,0
Exp/Cntr(USF)=0,0
Exp/Cntr=0.3,0.1

Type RM Length L Ch R = 1 ,3613    ,241.3,240.6,239.8
XS GIS Cut Line= 2
2261651.67257002622685.893229229 2261875.3389381622510.208095227
#Sta/Elev= 28
       0 2026.64     5.7 2026.67    14.1 2026.54    36.2 2026.41    46.5 2026.19
    74.9 2026.12    85.3 2025.95   109.1 2025.86   137.1 2025.35   148.1 2025.29
   163.4 2025.43   182.5 2025.32   191.7 2025.11   195.4 2025.15     199 2025.04
  205.09 2024.27   208.8  2023.8   211.7 2023.96   214.8 2024.28   223.1 2024.72
   225.9  2025.1   234.5  2026.9   249.9 2030.85     255 2031.98   265.1 2034.52
   270.2 2035.57     280 2037.42 284.415 2037.62
#Mann= 4 ,-1,0
       0    .055       0  205.09    .045       0   214.8    .055       0
     220     .05       0
Bank Sta=205.09,214.8
XS Rating Curve= 0 ,0
Exp/Cntr(USF)=0,0
Exp/Cntr=0.3,0.1

Type RM Length L Ch R = 1 ,3372    ,181.6,181.9,180.8
XS GIS Cut Line= 2
2261814.28482055622892.6237037952262038.19724621622672.812238307
#Sta/Elev= 30
       0 2025.89    16.3 2025.77    20.7 2025.62    44.9 2025.19    56.3 2024.86
    74.5 2024.16    99.9 2023.76   119.7 2023.73     126 2023.94   147.7  2023.8
   153.4 2023.97   156.5 2023.91   162.2 2024.01   173.5 2023.83   187.6 2024.09
   198.8 2023.78   204.6 2024.08  207.282023.705   210.3 2023.26   215.6 2023.06
   221.6 2023.72   227.2 2024.07   232.5    2025   249.3 2028.87   261.2 2031.37
   284.7 2036.61   294.1 2038.15   300.8 2038.91   307.5 2039.29   313.8 2039.39
#Mann= 4 ,-1,0
       0    .055       0      70     .05       0  207.28    .045       0
   221.6     .05       0
Bank Sta=207.28,221.6
XS Rating Curve= 0 ,0
Exp/Cntr(USF)=0,0
Exp/Cntr=0.3,0.1

Type RM Length L Ch R = 1 ,3190    ,161.8,163.1,162.7
XS GIS Cut Line= 3
2261949.61650639 623025.494813532262134.15971436622822.907380786
2262262.92986391622774.516050697
#Sta/Elev= 30
       0  2025.2    27.5 2025.06    47.3 2024.76    75.1 2023.74   109.6 2022.95
   123.8 2023.24   141.1 2023.09   157.8 2023.44   166.3 2023.44   177.6 2023.82
   183.3 2023.79   189.8 2024.17   195.2  2025.4   200.2 2025.04   208.7 2023.57
  212.492022.709   214.4 2022.32   216.9 2022.14   220.1 2022.71   227.7  2023.6
   235.5 2023.73   249.3 2024.94     279 2026.03   289.4 2025.97   297.6 2026.34
   311.1 2027.45   340.3 2029.39   370.4  2032.3   391.6  2034.7   411.6 2035.84
#Mann= 4 ,-1,0
       0    .055       0     110     .05       0  212.49    .045       0
   220.1     .05       0
Bank Sta=212.49,220.1
XS Rating Curve= 0 ,0
Exp/Cntr(USF)=0,0
Exp/Cntr=0.3,0.1

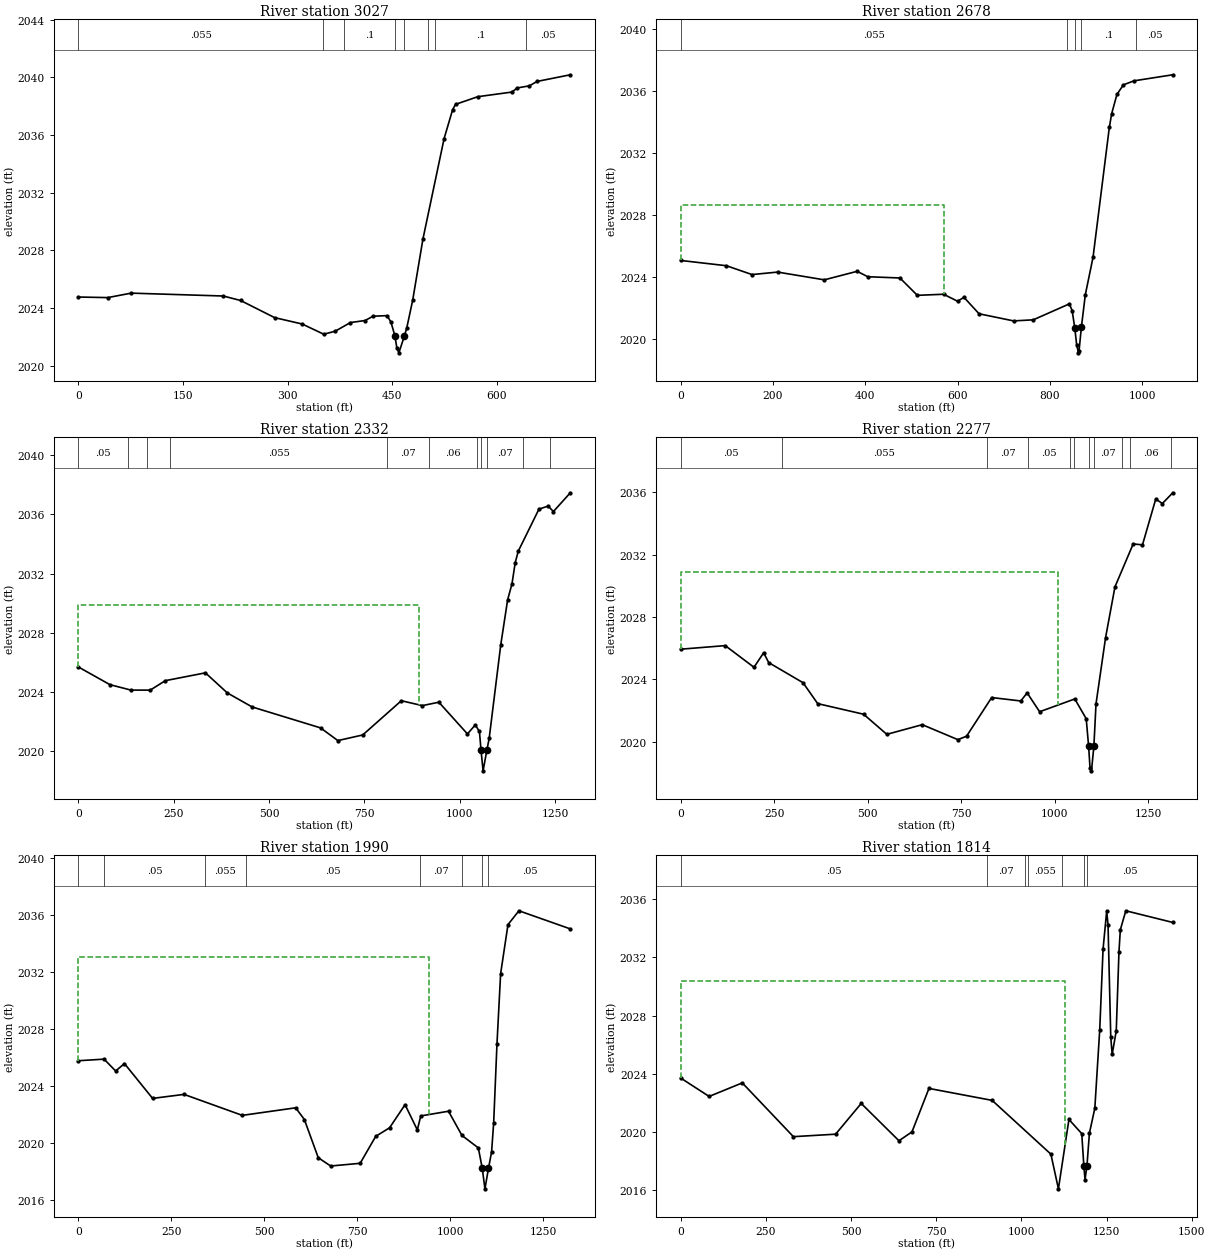
Type RM Length L Ch R = 1 ,3027    ,347.9,348.6,349.1
XS GIS Cut Line= 4
2261822.58674019623067.7437362742262046.92538736623122.971763068
2262231.61579086622953.5118873222262399.82897051622805.789506986
#Sta/Elev= 30
       0 2024.77    42.2 2024.73    75.8 2025.04   207.9 2024.84   232.7 2024.53
   281.6 2023.34     321  2022.9     352 2022.19   368.4  2022.4   390.2    2023
   411.2 2023.14   422.7 2023.44   442.7 2023.48   448.3 2023.04     454 2022.08
   456.8 2021.24   459.7  2020.9  467.572022.054     471 2022.62   479.5 2024.54
   494.3 2028.81   524.6 2035.76   536.8 2037.76     541 2038.13   572.9 2038.66
   621.6 2038.98   629.7 2039.27   646.7 2039.41     658 2039.72   705.6 2040.18
#Mann= 8 ,-1,0
       0    .055       0  351.04     .05       0  381.04      .1       0
     454    .045       0  467.57      .1       0  501.69     .05       0
  511.69      .1       0  641.69     .05       0
Bank Sta=454,467.57
XS Rating Curve= 0 ,0
Exp/Cntr(USF)=0,0
Exp/Cntr=0.3,0.1

Type RM Length L Ch R = 1 ,2678    ,348,346.7,347.6
XS GIS Cut Line= 3
2261735.96196868623121.665419209 2262214.7772067623407.569989712
2262616.76459715623095.964659568
#Sta/Elev= 30
       0 2025.06      99 2024.72   154.4 2024.15   209.9 2024.31   311.1 2023.81
   382.3 2024.36   405.3 2024.01     475 2023.93   512.7 2022.81   569.6 2022.88
   599.9 2022.43   613.8 2022.68   646.5 2021.62   721.4 2021.16     764 2021.23
   842.3 2022.26   848.3 2021.82     854 2020.69     858 2019.63   861.9  2019.1
   863.1 2019.19   868.2 2020.74   876.8 2022.85   893.5 2025.26   928.9 2033.66
     934 2034.54   945.3 2035.77   959.3 2036.39   982.3 2036.65  1066.3 2037.04
#Mann= 5 ,-1,0
       0    .055       0  837.68     .05       0     854    .045       0
   868.2      .1       0  987.68     .05       0
#XS Ineff= 2 , 0
          570.59 2028.66
Permanent Ineff=
       F       F
Bank Sta=854,868.2
XS Rating Curve= 0 ,0
Exp/Cntr(USF)=0,0
Exp/Cntr=0.3,0.1

Type RM Length L Ch R = 1 ,2332    ,53.8,55,54.2
XS GIS Cut Line= 4
2261656.25201572623152.1617074962262477.66872145623620.329994009
2262642.27691855623488.1797512682262740.80999428623397.761164129
#Sta/Elev= 30
       0 2025.67    82.8 2024.47     138  2024.1   188.7  2024.1   228.2 2024.74
   333.3 2025.27   390.7 2023.91   455.7 2022.96   635.3 2021.54   680.6 2020.68
   745.8 2021.06   847.1 2023.38   902.3 2023.05   945.5 2023.28  1020.5 2021.13
    1041 2021.74  1051.9  2021.3 1056.162020.029  1061.5 2018.63 1071.42 2020.03
  1077.5 2020.83  1107.7 2027.14  1125.9 2030.22  1137.3  2031.3  1145.8 2032.74
  1153.9 2033.52    1208 2036.36    1232 2036.57    1246  2036.2  1290.3 2037.47
#Mann= 11 ,-1,0
       0     .05       0     130    .055       0     180     .05       0
     240    .055       0     810     .07       0     920     .06       0
 1045.47     .07       0 1056.16    .045       0 1071.42     .07       0
 1166.56     .06       0 1236.56     .05       0
#XS Ineff= 2 , 0
          893.57 2029.87
Permanent Ineff=
       F       F
Bank Sta=1056.16,1071.42
XS Rating Curve= 0 ,0
Exp/Cntr(USF)=0,0
Exp/Cntr=0.3,0.1

Type RM Length L Ch R = 1 ,2277    ,277.2,286.7,292.9
XS GIS Cut Line= 4
2261627.91825451623224.9321753482262487.83503963623676.964371591
2262652.44323672 623544.814128852262750.97631245623454.395541711
#Sta/Elev= 30
       0 2025.94   118.9 2026.17   195.9 2024.78   221.7 2025.71   235.3 2025.08
   327.2 2023.79   366.3 2022.45   489.1 2021.77   551.3 2020.48   646.1  2021.1
   741.4 2020.14   764.6 2020.36   831.8 2022.84   909.7 2022.62   926.7 2023.14
   960.1 2021.93  1054.2 2022.75  1084.8 2021.48 1091.142019.728    1095 2018.32
  1098.9 2018.14 1105.272019.728    1111 2022.44  1136.6 2026.69  1161.7 2029.94
  1210.4 2032.69  1235.3 2032.63  1270.8 2035.57  1288.5 2035.28  1316.3 2035.97
#Mann= 11 ,-1,0
       0     .05       0     270    .055       0     820     .07       0
     930     .05       0 1041.49     .06       0 1051.49     .07       0
 1091.14    .045       0 1105.27     .07       0 1181.49     .05       0
 1202.58     .06       0 1312.58     .07       0
#XS Ineff= 2 , 0
         1008.81 2030.87
Permanent Ineff=
       F       F
Bank Sta=1091.14,1105.27
XS Rating Curve= 0 ,0
Exp/Cntr(USF)=0,0
Exp/Cntr=0.3,0.1

Type RM Length L Ch R = 1 ,1990    ,175.5,176.5,177.4
XS GIS Cut Line= 4
 2261569.7174646623305.5827337172262429.58515628623820.468036882
2262541.65512329623877.5359150772262727.81270793623937.628153903
#Sta/Elev= 30
       0 2025.79    69.3  2025.9   100.4 2025.07   124.1 2025.59   199.8 2023.15
   284.4 2023.43   441.1 2021.96   584.7 2022.49   608.1 2021.67   645.5 2018.99
   678.9 2018.41   758.2  2018.6   800.1 2020.49   837.4 2021.09     879 2022.71
     912 2020.94   921.3 2021.92   995.9 2022.25  1032.1 2020.55  1076.1 2019.68
 1086.72 2018.24  1093.9 2016.81 1103.382018.239  1111.8  2019.4  1117.4 2021.44
  1126.3 2026.98  1136.1 2031.89  1155.9 2035.33  1185.3  2036.3  1323.6 2035.03
#Mann= 8 ,-1,0
       0     .06       0      70     .05       0     340    .055       0
     450     .05       0     920     .07       0 1032.24     .05       0
 1086.72    .045       0 1103.38     .05       0
#XS Ineff= 2 , 0
           943.4 2033.05
Permanent Ineff=
       F       F
Bank Sta=1086.72,1103.38
XS Rating Curve= 0 ,0
Exp/Cntr(USF)=0,0
Exp/Cntr=0.3,0.1

Type RM Length L Ch R = 1 ,1814    ,269.4,265,258.1
XS GIS Cut Line= 4
2261344.74772178623500.3679695432262385.29313488623989.515452075
2262453.90450889624035.1235285582262665.48703188624052.573633546
#Sta/Elev= 30
       0 2023.71    83.3 2022.45   180.6 2023.38   330.7 2019.69   454.6 2019.86
   529.8 2021.97   640.6 2019.41   678.9 2020.02   728.7    2023   914.2 2022.18
  1086.7 2018.49  1108.8 2016.11  1139.7 2020.87  1177.3  2019.9 1183.362017.711
  1186.9 2016.74 1192.652017.705  1199.8 2019.93  1215.7 2021.64  1230.1 2027.03
  1239.9 2032.57  1250.5 2035.16  1254.5 2034.22  1262.5 2026.51  1266.6 2025.34
  1278.6 2026.95  1286.6 2032.39  1290.6 2033.89  1306.7 2035.19  1444.5 2034.39
#Mann= 7 ,-1,0
       0     .05       0     900     .07       0    1010     .08       0
    1020    .055       0    1120     .05       0 1183.36    .045       0
 1192.65     .05       0
#XS Ineff= 2 , 0
         1128.45 2030.38
Permanent Ineff=
       F       F
Bank Sta=1183.36,1192.65
XS Rating Curve= 0 ,0
Exp/Cntr(USF)=0,0
Exp/Cntr=0.3,0.1

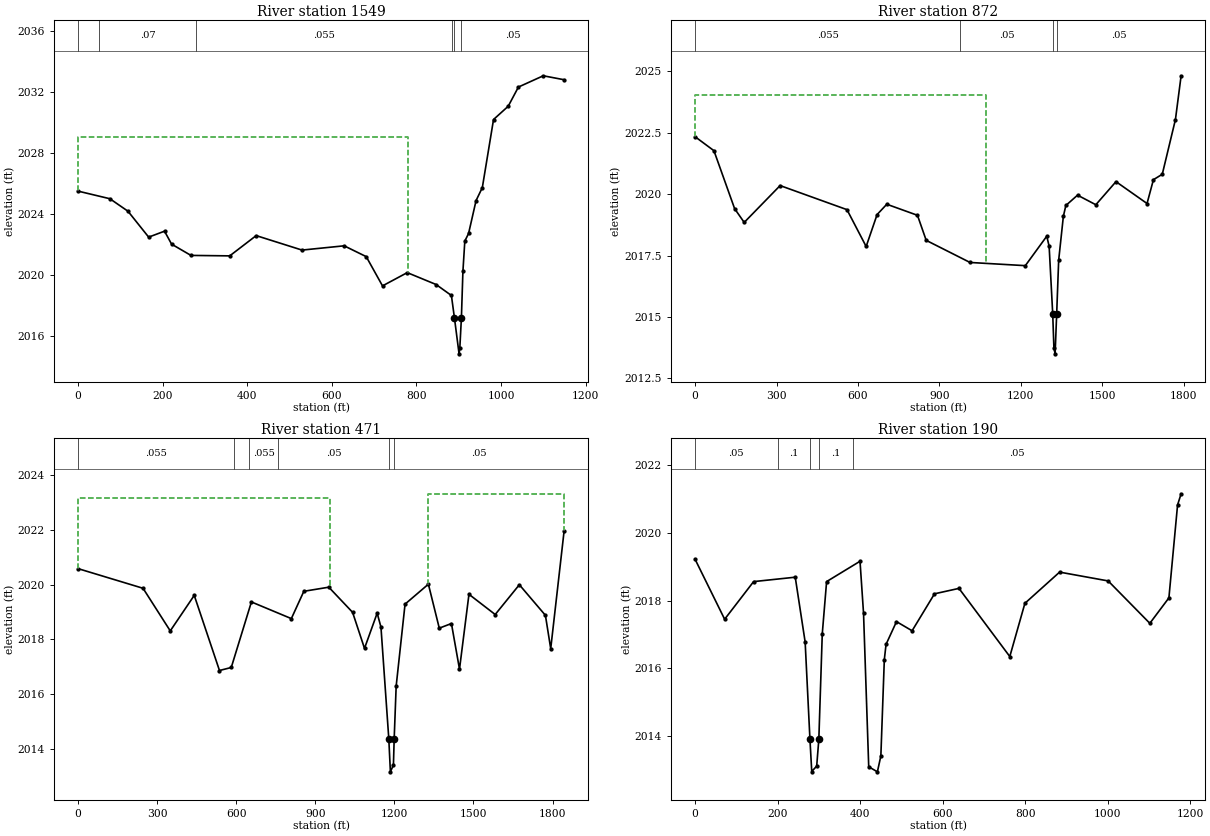
Type RM Length L Ch R = 1 ,1549    ,676.5,677,677.4
XS GIS Cut Line= 3
2261623.93156429624147.9975595622262281.38663592624340.501075904
2262691.63057251624123.395122783
#Sta/Elev= 30
       0  2025.5    75.3    2025   118.1 2024.18     167 2022.48   204.5 2022.87
   221.2 2022.02     267 2021.28   358.7 2021.25   421.2 2022.58   529.6 2021.63
   629.2 2021.91   681.4  2021.2   719.9 2019.28   778.4 2020.15   846.6 2019.37
   882.8 2018.65  889.962017.179   900.9 2014.82   902.7  2015.2  906.422017.182
     910 2020.23   914.5 2022.22   923.4 2022.72   941.1 2024.88   955.9 2025.73
   982.4  2030.2  1017.1 2031.07  1041.2 2032.33    1100 2033.07  1149.2 2032.81
#Mann= 6 ,-1,0
       0    .055       0      50     .07       0     280    .055       0
  885.06     .05       0  889.96    .045       0  906.42     .05       0
#XS Ineff= 2 , 0
          780.65 2029.05
Permanent Ineff=
       F       F
Bank Sta=889.96,906.42
XS Rating Curve= 0 ,0
Exp/Cntr(USF)=0,0
Exp/Cntr=0.3,0.1

Type RM Length L Ch R = 1 ,872     ,403.6,401.1,398.5
XS GIS Cut Line= 6
 2261676.8773188624404.3041711652262323.57642009 624950.95990116
2262540.20939559624922.4214253462262614.44005902624913.892964103
2262820.27931252624821.1446890582263030.53014405624452.332952474
#Sta/Elev= 30
       0 2022.34    69.5 2021.77   145.7 2019.41     181 2018.85   313.3 2020.35
   559.5 2019.37   630.2 2017.87   670.5 2019.17   706.2 2019.59   819.2 2019.14
   851.4 2018.12  1012.8 2017.22  1216.5 2017.09  1295.5 2018.29  1304.2 2017.88
  1317.3 2015.14  1321.8 2013.74  1326.2  2013.5 1331.99 2015.14  1339.3 2017.31
  1356.6  2019.1  1365.8 2019.54  1408.8 2019.96  1476.2 2019.57  1550.4 2020.51
  1664.8 2019.62  1688.3 2020.59  1720.9 2020.81  1769.4 2023.04  1790.3 2024.82
#Mann= 4 ,-1,0
       0    .055       0  976.79     .05       0  1317.3    .045       0
 1331.99     .05       0
#XS Ineff= 2 , 0
         1073.11 2024.03
Permanent Ineff=
       F       F
Bank Sta=1317.3,1331.99
XS Rating Curve= 0 ,0
Exp/Cntr(USF)=0,0
Exp/Cntr=0.3,0.1

Type RM Length L Ch R = 1 ,471     ,271.4,280.8,284.2
XS GIS Cut Line= 4
2261781.70547995 624743.467755872262745.70285148625248.546014884
2262883.55980749625156.4837309852263109.11329076624611.768335667
#Sta/Elev= 30
       0 2020.59   246.6 2019.87   349.8 2018.31   440.8 2019.61   536.5 2016.86
   581.2 2016.97   657.6 2019.37   809.1 2018.76   856.5 2019.76   951.1 2019.91
  1041.4 2018.99  1086.6 2017.67  1134.6 2018.96    1149 2018.45  1178.72014.367
  1184.8 2013.15  1196.3  2013.4  1199.2 2014.37  1206.7 2016.29  1240.4 2019.29
  1328.9 2020.02  1370.2 2018.41  1416.3 2018.58  1446.9 2016.91  1482.8 2019.65
  1582.3 2018.91  1673.9    2020  1772.8 2018.88  1792.9 2017.66  1843.6 2021.96
#Mann= 6 ,-1,0
       0    .055       0     590     .05       0     650    .055       0
     760     .05       0  1178.7    .045       0  1199.2     .05       0
#XS Ineff= 2 , 0
          954.51 2023.18 1325.63         2023.33
Permanent Ineff=
       F       F
Bank Sta=1178.7,1199.2
XS Rating Curve= 0 ,0
Exp/Cntr(USF)=0,0
Exp/Cntr=0.3,0.1

Type RM Length L Ch R = 1 ,190     ,,,
XS GIS Cut Line= 4
2262699.18589643 625308.407950342262903.98013226625430.769286212
 2263017.3253697625430.7692862122263272.35215394624645.080708507
#Sta/Elev= 30
       0 2019.22    71.7 2017.45   141.9 2018.56   242.8 2018.69   266.8 2016.78
   278.42013.917   282.8 2012.96   294.8 2013.12  299.972013.909   308.3 2017.02
   318.8 2018.56   399.8 2019.16   408.3 2017.63   420.9  2013.1   441.9 2012.95
   450.3 2013.42   458.7 2016.26   462.9 2016.71   488.2 2017.38     526 2017.11
   580.3  2018.2   639.6 2018.36   762.8 2016.35   799.4 2017.92   883.5 2018.84
  1001.2 2018.58  1102.2 2017.33  1148.4 2018.08  1169.4 2020.82    1178 2021.15
#Mann= 5 ,-1,0
       0     .05       0     200      .1       0   278.4    .045       0
  299.97      .1       0  381.91     .05       0
Bank Sta=278.4,299.97
XS Rating Curve= 0 ,0
Exp/Cntr(USF)=0,0
Exp/Cntr=0.3,0.1
LCMann Table=0

Chan Stop Cuts=-1
Use User Specified Reach Order=0
Composite Channel Slope=5